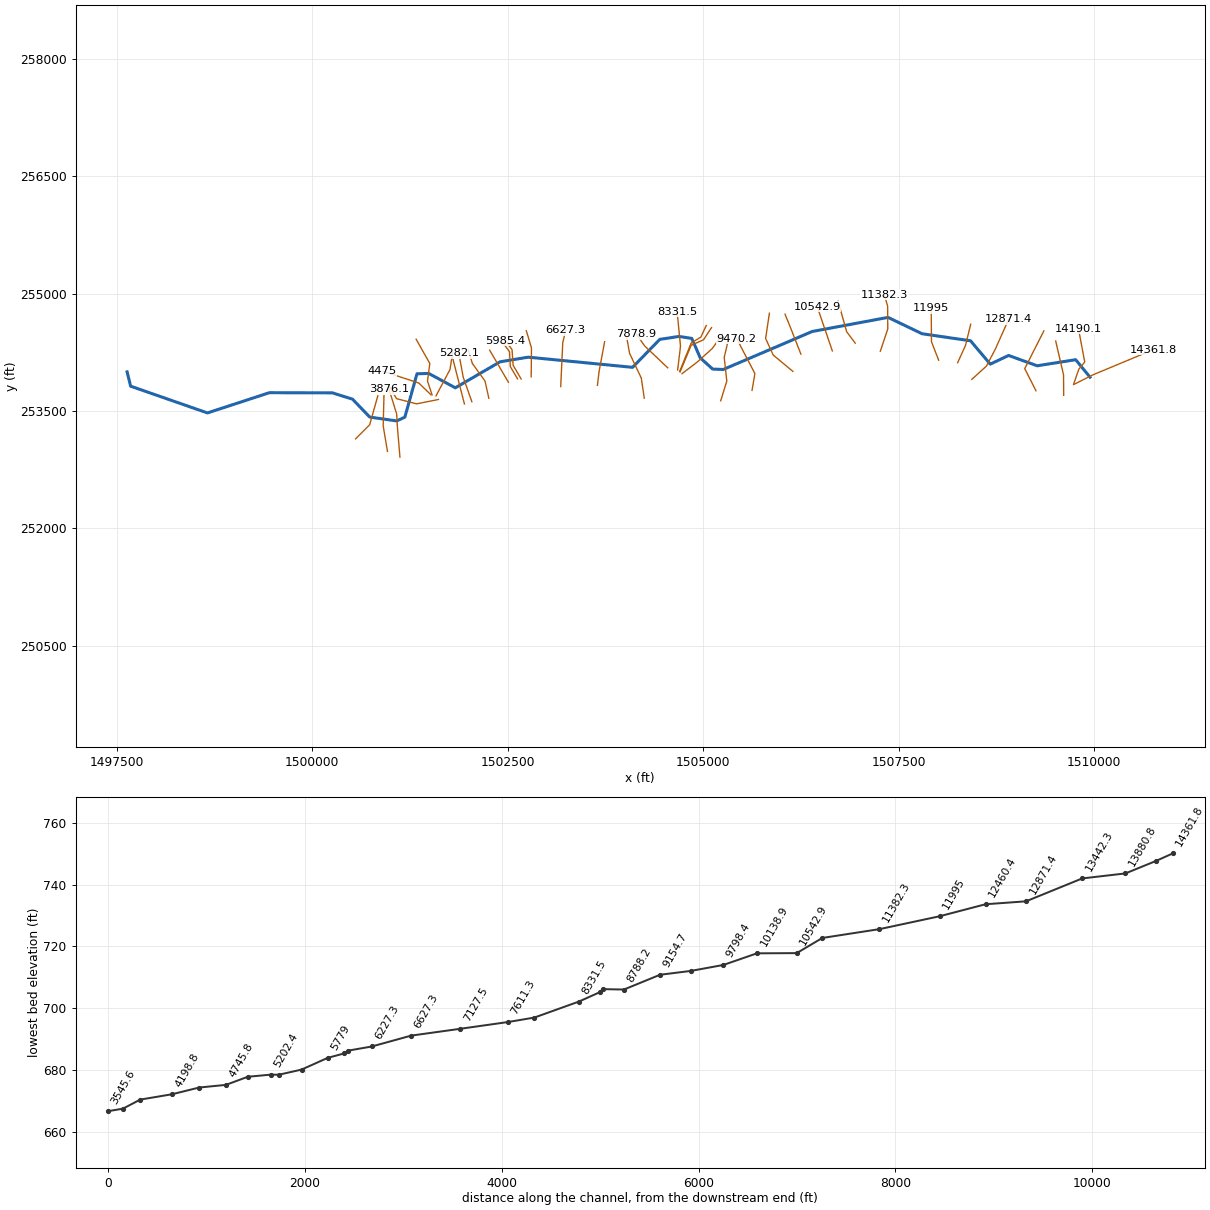
--- ADDSRN.prj (project) ---

Proj Title=ADDSRN
Current Plan=p01
Default Exp/Contr=0,0
English Units
Geom File=g01
Flow File=f01
Plan File=p01
BEGIN DESCRIPTION:
END DESCRIPTION:
DSS Export Rating Curves= 0
DSS Export Rating Curve Sorted= 0
DSS Export Volume Flow Curves= 0
DXF OffsetX= 0
DXF OffsetY= 0
DXF ScaleX= 0
DXF ScaleY= 0

--- ADDSRN.p01 (plan) ---

Plan Title=Floodplain
Program Version=4.00
Geom File=g01
Flow File=f01
K Sum by GR=0
Std Step Tol=0.01
Critical Tol=0.01
Num of Std Step Trials=20
Max Error Tol=0.3
Flow Tol Ratio=0.001
Split Flow NTrial=30
Split Flow Tol=0.02
Split Flow Ratio=0.02
Log Output Level=0
Friction Slope Method=1
Unsteady Friction Slope Method=2
Unsteady Bridges Friction Slope Method=1
Global Log Level=0
CheckData=False
Run HTab=0
Run UNet=0
Run PostProcess=0
UNET Theta=0
UNET Theta Warmup=0
UNET ZTol=0
UNET ZSATol=0
UNET MxIter=0
UNET MaxInSteps=0
UNET DtIC=0
UNET DtMin=0
UNET MaxCRTS=0
UNET WFStab=0
UNET SFStab=0
UNET WFX=0
UNET SFX=0
UNET DSS MLevel=0
UNET DZMax Abort=0
UNET Convert EG Bridges=0
UNET Use Existing IB Tables=0
UNET Froude Limit=0
UNET Froude Power=0
Write IC File=0
Echo Input=False
Echo Output=False
Write Detailed=0

--- ADDSRN.f01 (steady flow) ---

Flow Title=NFF Regression Equation
Program Version=4.10
Number of Profiles= 1
Profile Names=P100yr
River Rch & RM=ADDSRN,Main            ,14361.8
757.2417
River Rch & RM=ADDSRN,Main            ,13880.8
1034.282
River Rch & RM=ADDSRN,Main            ,12871.4
1143.925
River Rch & RM=ADDSRN,Main            ,11382.3
1264.775
River Rch & RM=ADDSRN,Main            ,9798.4
1306.122
River Rch & RM=ADDSRN,Main            ,4968.1
1421.919
River Rch & RM=ADDSRN,Main            ,616.4
 1578.84
River Rch & RM=ADDSRN,Main            ,227.2
1581.517
Boundary for River Rch & Prof#=ADDSRN,Main            , 1
Up Type= 0
Dn Type= 3
Dn Slope=0.00412
DSS Import GetInterval= 0
DSS Import GetPeak= 0
DSS Import FillOption= 0

--- ADDSRN.g01 (geometry) ---

Geom Title=USGS 10m DEM
Program Version=4.10

River Reach=ADDSRN          ,Main
Reach XY= 30
     1509949.688      253932.039      1509765.77      254155.486
     1509273.836      254077.881     1508907.975      254209.795
     1508673.296       254098.89      1508420.91      254397.459
     1507801.622      254487.007     1507366.143      254696.232
     1506394.991      254515.675     1505258.833      254030.374
     1505123.295      254035.695     1504964.962      254178.057
     1504855.175      254428.312     1504691.135      254452.612
     1504446.701      254415.357     1504098.295      254057.918
     1502764.104      254187.764     1502403.826      254128.647
     1501831.322      253796.115     1501490.657       253980.14
     1501340.959      253975.426     1501185.592      253421.031
     1501081.629      253373.195      1500736.49      253422.501
     1500516.317      253651.092     1500259.445      253731.601
     1499453.343      253733.859     1498660.796      253475.279
      1497678.11       253817.25     1497633.264      253999.842

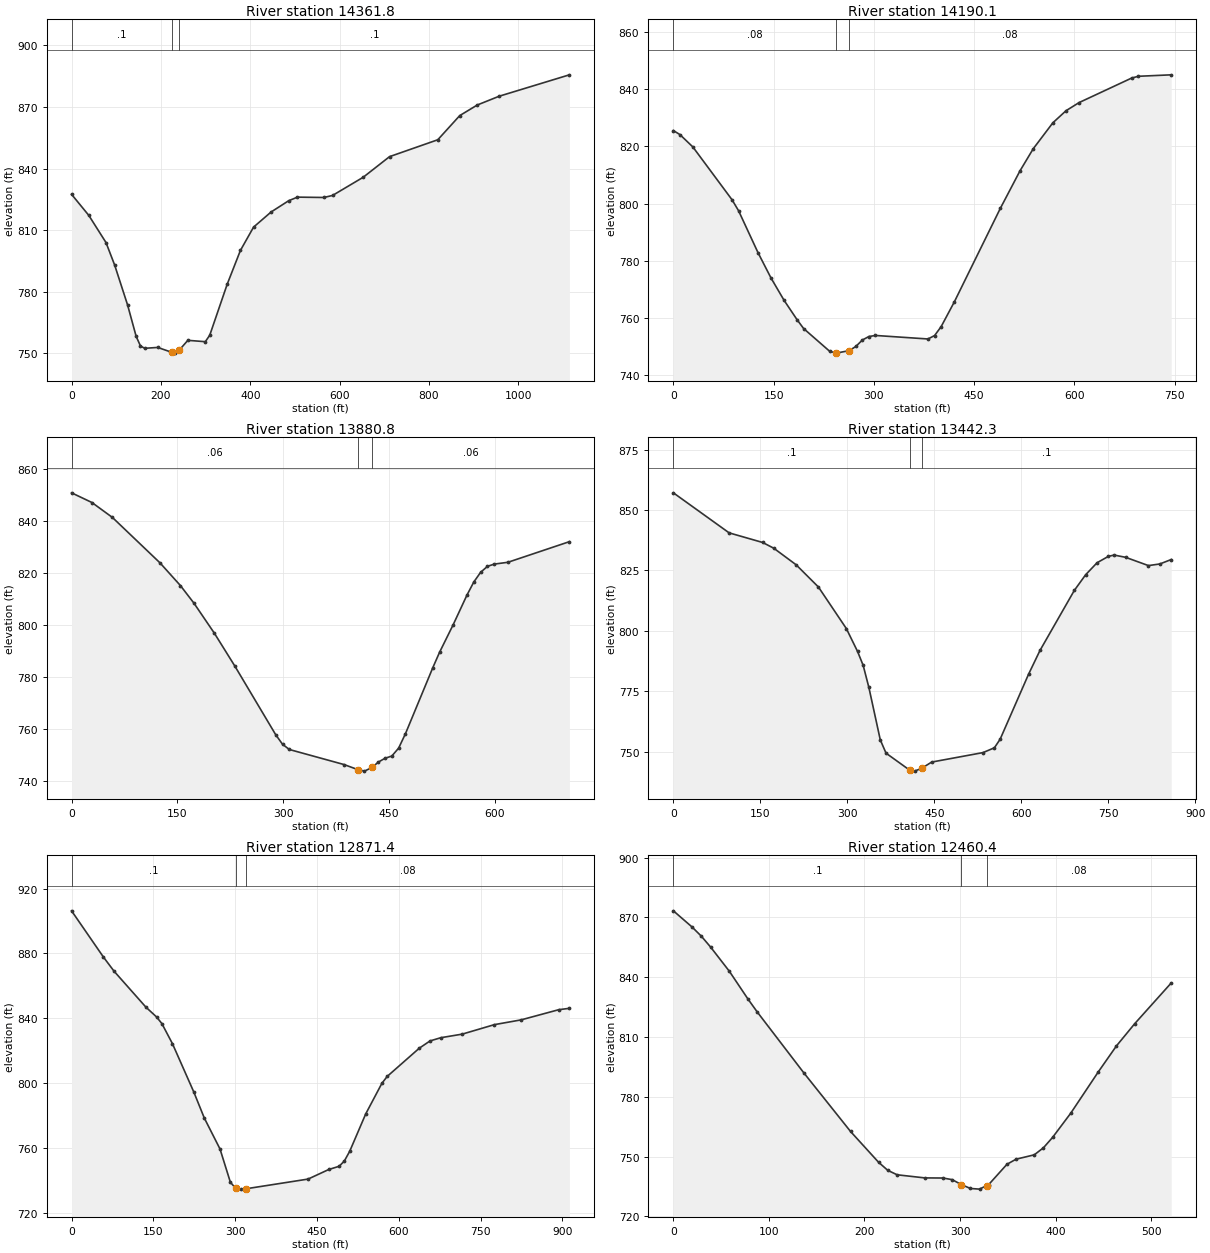
Type RM Length L Ch R = 1 ,14361.8 ,161.3,171.7,182
XS GIS Cut Line= 3
     1509739.683      253837.816     1509980.694      253959.489
     1510760.208      254284.142
#Sta/Elev= 30
       0  827.46    38.6   817.2    77.1  803.97    96.4  793.06   125.4  773.59
   144.6  758.29   154.3  753.59   163.9  752.48   192.8   752.9  224.99750.4821
   231.4  750.13   241.1   751.6   260.3  756.36   299.4   755.7   309.3  758.83
   348.5  783.75     378  800.14   407.4  811.49   446.7  818.86     486  824.34
   505.6  826.09   564.6  825.92   584.2  826.91   652.9  835.78   711.8  845.81
   819.8  854.03   868.9  865.79   908.2  870.96   957.3  875.24  1114.4  885.65
#Mann= 3 , 0 , 0
       0      .1       0  224.99    .045       0   241.1      .1       0
Bank Sta=224.99,241.1
XS Rating Curve= 0 ,0
Exp/Cntr=0.3,0.1

Type RM Length L Ch R = 1 ,14190.1 ,285.9,309.3,332.5
XS GIS Cut Line= 4
     1509742.846       253851.85     1509807.083      254035.878
     1509881.735      254126.156     1509801.874      254551.503
#Sta/Elev= 30
       0  825.51     9.8  824.11    29.2  819.77    87.7  801.33    97.5  797.49
   126.7  782.77   146.2  773.89   165.7  766.11   185.2  759.31   194.9  756.26
     234  748.28   243.7  747.67   263.2  748.55     273  750.01   282.8  752.27
   292.5  753.48   302.3  753.85   380.9  752.62   390.8  753.82   400.6  756.94
   420.3  765.58   489.1  798.29   518.6  811.44   538.3  819.13   567.8  828.25
   587.5  832.47   607.1  835.32   685.8   843.9   695.7   844.5   744.8  845.01
#Mann= 3 , 0 , 0
       0     .08       0   243.7    .045       0   263.2     .08       0
Bank Sta=243.7,263.2
XS Rating Curve= 0 ,0
Exp/Cntr=0.3,0.1

Type RM Length L Ch R = 1 ,13880.8 ,455.7,438.5,420.5
XS GIS Cut Line= 3
     1509612.638      253700.809     1509610.902      253961.225
     1509510.208      254395.253
#Sta/Elev= 30
       0  850.79    28.9  847.06    57.9  841.32   125.4  823.83   154.3  815.11
   173.6   808.3   202.6  796.71   231.5  784.12   289.5  757.67   299.2  753.99
   308.8  751.98   386.3  746.19   406.3744.2032   415.4  743.65   426.3745.0745
   434.8  747.09   444.5   748.6   454.1  749.45   463.8  752.49   473.5  758.06
   512.3  783.48   521.9  789.42   541.3  800.08   560.7  811.41   570.4  816.45
   580.1  820.19   589.8  822.49   599.4  823.35   618.8  824.05     706  831.99
#Mann= 3 , 0 , 0
       0     .06       0   406.3    .045       0   426.3     .06       0
Bank Sta=406.3,426.3
XS Rating Curve= 0 ,0
Exp/Cntr=0.3,0.1

Type RM Length L Ch R = 1 ,13442.3 ,569.7,570.9,569.2
XS GIS Cut Line= 3
     1509258.471        253758.1     1509114.374      254041.086
     1509359.166      254523.725
#Sta/Elev= 30
       0  857.11    96.2  840.55     154  836.58   173.2   834.2   211.7  827.36
   250.2  818.16   298.3     801   317.6  791.56   327.4  785.74   337.2  776.64
   356.9  754.94   366.8  749.46     408742.3622     416  742.03     428743.1602
   445.5  745.77     534  749.69   553.7  751.68   563.6  755.22   612.7  782.13
   632.4  791.96   691.5  816.73   711.1  823.24   730.8   828.2   750.5  830.86
   760.3  831.37     780  830.45   819.4  827.02     839  827.69   858.7  829.53
#Mann= 3 , 0 , 0
       0      .1       0     408    .045       0     428      .1       0
Bank Sta=408,428
XS Rating Curve= 0 ,0
Exp/Cntr=0.3,0.1

Type RM Length L Ch R = 1 ,12871.4 ,405.3,411,416.6
XS GIS Cut Line= 4
     1508437.291      253903.934     1508624.791      254074.072
     1508739.374      254292.822     1508907.777      254669.559
#Sta/Elev= 30
       0  906.27    58.4  877.77    77.9  869.04   136.3  846.87   155.8  840.83
   165.6  836.72     185  824.32     224  794.63   243.4  778.46   272.2  759.36
   291.2  738.86   300.7  735.21   310.2  734.62   319.7  734.83   433.6  740.81
   471.6  746.73   490.6  748.71   500.1  751.93     510  757.97   539.4  781.05
   568.9  799.82   578.7  804.13   637.7  821.58   657.3  826.03     677  828.01
   716.3  830.22   775.2  836.07   824.4  839.02   893.1  845.28   912.8  846.14
#Mann= 3 , 0 , 0
       0      .1       0   300.7    .045       0   319.7     .08       0
Bank Sta=300.7,319.7
XS Rating Curve= 0 ,0
Exp/Cntr=0.3,0.1

Type RM Length L Ch R = 1 ,12460.4 ,459,465.5,471.5
XS GIS Cut Line= 3
     1508256.735      254117.475      1508357.43      254339.697
     1508423.402      254608.795
#Sta/Elev= 30
       0  873.27    19.5  865.18    29.3  860.53      39  855.07    58.6  842.94
    78.1     829    87.8  822.51   136.6  791.94   185.4   762.6   214.7  747.17
   224.4  743.08   234.2  740.86   263.1   739.3   282.2  739.24   291.7  738.43
   301.3  735.99   310.8     734   320.4  733.67   327.9735.4578     330  735.96
   349.1  746.13   358.6  748.68   377.7  750.88   387.3  754.42   396.8  759.59
   415.9  771.79   444.6  792.42   463.7  805.52   482.8  816.66     521  837.08
#Mann= 3 , 0 , 0
       0      .1       0   301.3    .045       0   327.9     .08       0
Bank Sta=301.3,327.9
XS Rating Curve= 0 ,0
Exp/Cntr=0.3,0.1

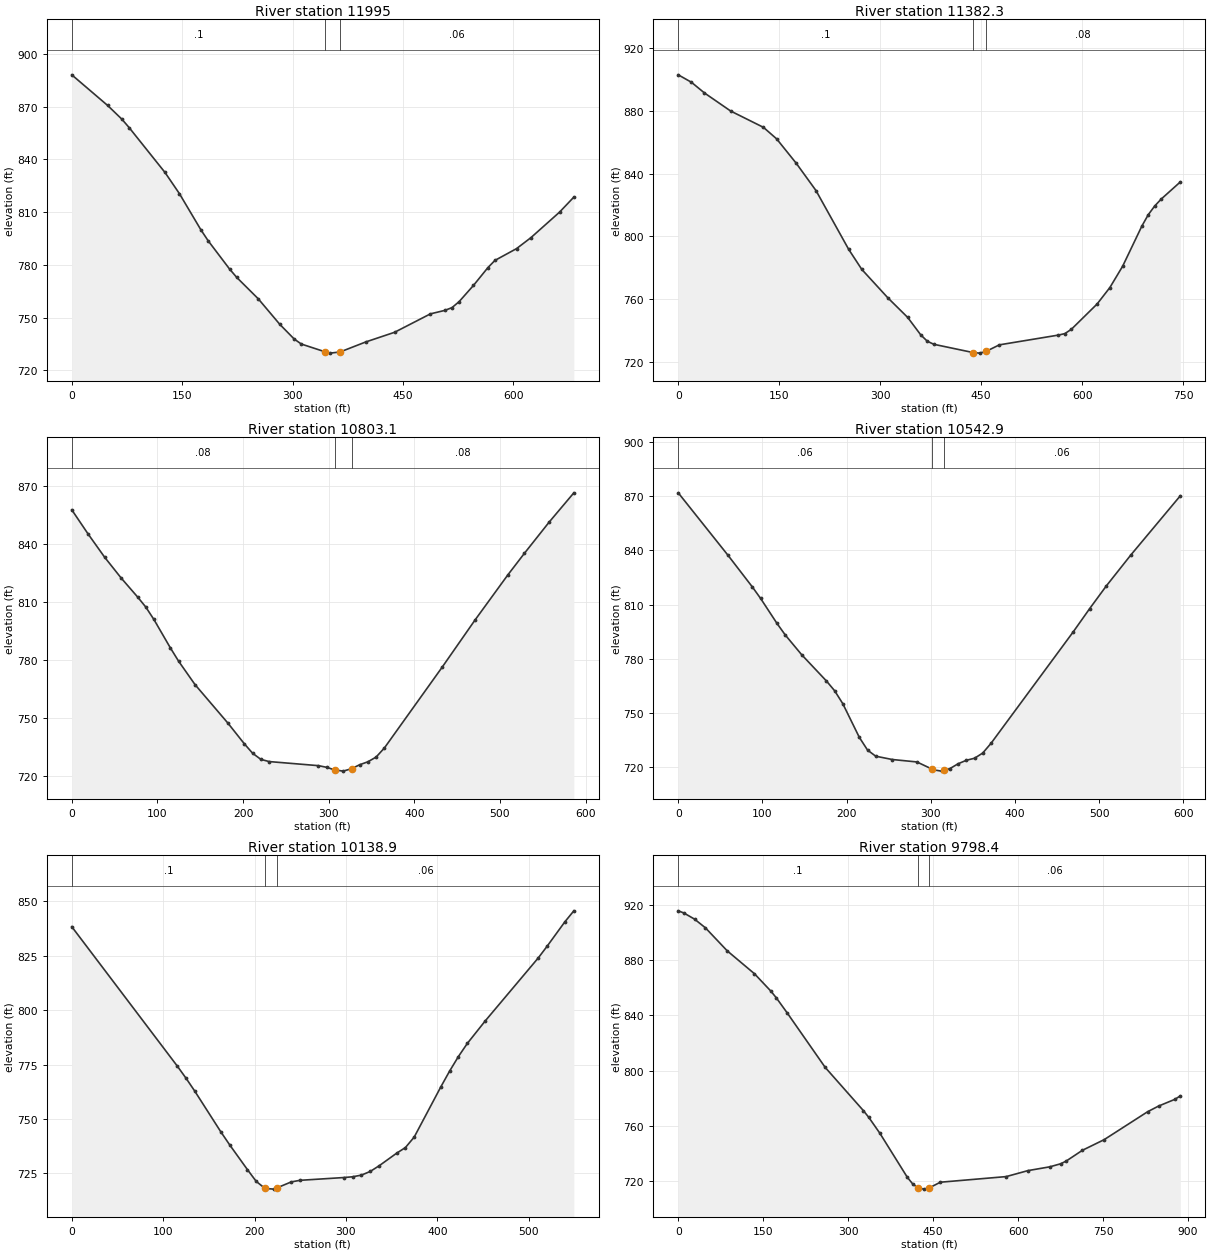
Type RM Length L Ch R = 1 ,11995   ,612.6,612.7,612.5
XS GIS Cut Line= 3
      1508013.68      254148.725     1507921.666      254384.836
     1507918.194      254813.656
#Sta/Elev= 30
       0  888.09    48.7  870.68    68.2  862.81      78  858.05   126.7  832.54
   146.2  820.55   175.4  799.96   185.2  793.77   214.4  777.63   224.2  772.84
   253.4  760.69   282.6  746.19   302.1  737.86   311.9  734.96   344.5730.4911
   350.9  729.79   364.5730.4344   399.6  736.17   438.6  741.64   487.3  752.12
   506.8  754.09   516.6  755.66   526.3  759.07   545.8  768.29   565.3  778.37
     575  782.54   604.3  789.22   623.8  795.45   662.8     810   682.2  818.54
#Mann= 3 , 0 , 0
       0      .1       0   344.5    .045       0   364.5     .06       0
Bank Sta=344.5,364.5
XS Rating Curve= 0 ,0
Exp/Cntr=0.3,0.1

Type RM Length L Ch R = 1 ,11382.3 ,572.3,579.2,585.6
XS GIS Cut Line= 4
     1507267.152      254263.309     1507362.638      254549.767
     1507360.902      254841.434     1507317.499      254987.267
#Sta/Elev= 30
       0  903.09    19.5  898.38      39  891.51    77.9     880   126.6  869.59
   146.1  862.28   175.3  846.69   204.6   829.3   253.2  791.78   272.7  778.98
   311.7  760.73   340.8   748.4   360.3  737.22     370  733.19   379.7  731.24
   438.4725.9393   447.8  725.61   457.5  726.76     477  730.89   564.5   737.1
   574.2  738.04   583.9  740.78   622.2  756.94   641.2  767.45   660.2  781.08
   688.7  806.64   698.2  813.89   707.7   819.4   717.2  823.77   745.8  834.78
#Mann= 3 , 0 , 0
       0      .1       0   438.4    .045       0   457.5     .08       0
Bank Sta=438.4,457.5
XS Rating Curve= 0 ,0
Exp/Cntr=0.3,0.1

Type RM Length L Ch R = 1 ,10803.1 ,258.9,260.3,261.7
XS GIS Cut Line= 3
     1506945.971      254367.475     1506836.596      254513.309
     1506727.221      254902.197
#Sta/Elev= 30
       0  857.66    19.2  845.09    38.4  833.17    57.6  822.48    76.8  812.69
    86.4  807.48    95.9  801.05   115.1  786.41   124.7  779.55   143.9  767.44
   182.3  747.56   201.5  736.87   211.2  731.98   220.8  728.83   230.4   727.7
   288.1  725.58   297.7  724.72   306.9723.3975     317  722.76   326.9 724.045
   336.2  726.06   345.8  727.58   355.4  730.02     365  734.67   432.4  776.34
   470.8   800.7   509.3   824.1   528.6  835.21   557.4  851.27   586.3  866.42
#Mann= 3 , 0 , 0
       0     .08       0   306.9    .045       0   326.9     .08       0
Bank Sta=306.9,326.9
XS Rating Curve= 0 ,0
Exp/Cntr=0.3,0.1

Type RM Length L Ch R = 1 ,10542.9 ,402.8,404,405
XS GIS Cut Line= 2
     1506653.907      254266.629     1506460.765      254830.865
#Sta/Elev= 30
       0  871.81    58.7   837.5      88  819.77    97.8  813.42   117.3  799.57
   127.1  793.19   146.6  782.26     176  767.74   185.8  762.31   195.5  755.14
   215.1  736.54   224.9  729.48   234.6  726.11   254.2  724.28   283.5  722.93
   301.3719.0062   303.1  718.58   312.8  717.85   315.4 718.214   322.6  719.22
   332.4  721.91   342.2  723.84     352  724.99   361.7  727.86   371.5   733.2
   469.3  794.96   488.8   807.8   508.4  820.24   537.7  837.46   596.4  870.17
#Mann= 3 , 0 , 0
       0     .06       0   301.3    .045       0   315.4     .06       0
Bank Sta=301.3,315.4
XS Rating Curve= 0 ,0
Exp/Cntr=0.3,0.1

Type RM Length L Ch R = 1 ,10138.9 ,339.1,340.5,341.9
XS GIS Cut Line= 3
     1506251.527       254226.85     1506110.902      254584.489
     1506048.402      254737.267
#Sta/Elev= 30
       0  838.41   115.3  774.43   124.9  768.84   134.5  762.89   163.3  743.99
   172.9  738.06   192.2  726.76   201.8  721.36   211.4  718.11     221  717.78
   224.7718.3907   240.2   721.1   249.8  721.83   297.8  723.11   307.4  723.46
     317  724.23   326.6  725.91   336.3   728.5   355.5   734.3   365.1  736.89
   374.7   741.7   403.7  764.67   413.4     772   423.1  778.73   432.8  784.73
   452.3  795.03   510.5  824.07   520.2  829.45   539.6  840.66   549.4   845.7
#Mann= 3 , 0 , 0
       0      .1       0   211.4    .045       0   224.7     .06       0
Bank Sta=211.4,224.7
XS Rating Curve= 0 ,0
Exp/Cntr=0.3,0.1

Type RM Length L Ch R = 1 ,9798.4  ,326.9,328.3,329.4
XS GIS Cut Line= 4
     1506149.096      254006.364      1505897.36      254214.697
     1505800.138      254426.503     1505848.749       254749.42
#Sta/Elev= 30
       0   915.9     9.6   914.4    28.8  909.88      48  903.57    86.5  886.87
   134.6  870.25   163.4  857.72     173  852.87   192.2  841.95   259.5   802.3
   326.8  771.01   336.5  766.02   355.9   754.6   404.4  722.63   414.2  717.65
   423.2714.9963   433.6  714.02   443.2714.9304   462.7  719.03     579  723.11
   617.4  727.45   655.9  730.19   675.1   732.4   684.7  734.32   713.5  742.18
   751.9   749.9   828.7  770.17     848  774.27   876.8  779.16   886.4  781.65
#Mann= 3 , 0 , 0
       0      .1       0   423.2    .045       0   443.2     .06       0
Bank Sta=423.2,443.2
XS Rating Curve= 0 ,0
Exp/Cntr=0.3,0.1

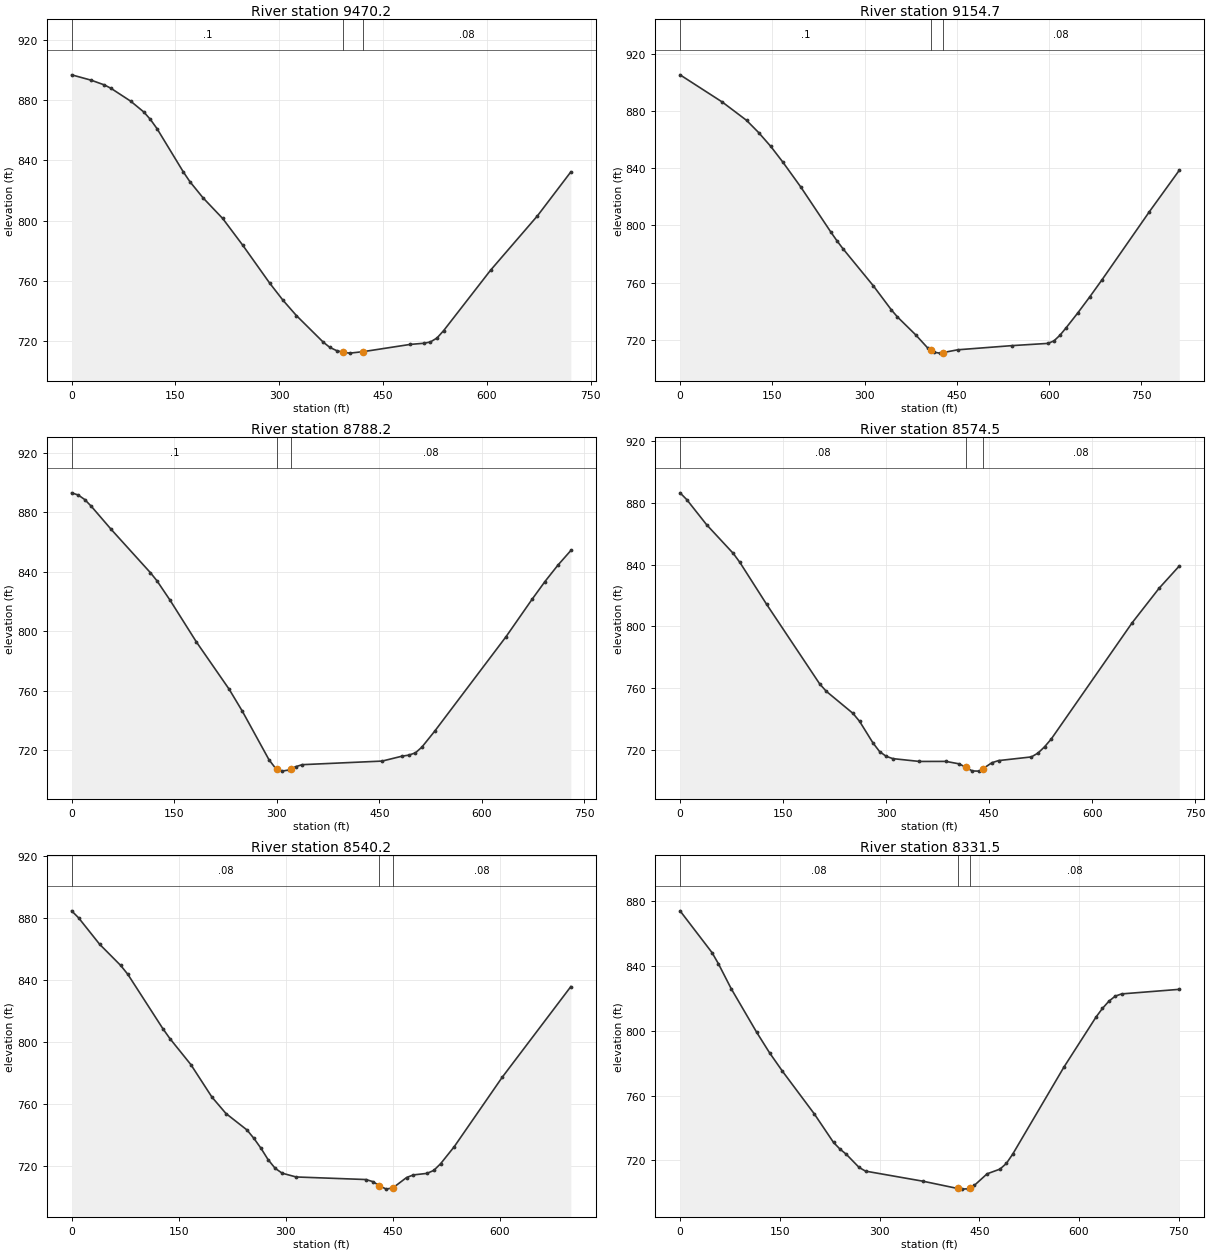
Type RM Length L Ch R = 1 ,9470.2  ,324.7,315.4,306.1
XS GIS Cut Line= 3
     1505626.527      253763.309     1505662.985      253978.586
     1505430.346      254424.767
#Sta/Elev= 30
       0  896.78    28.5  893.18    47.5  890.05      57  887.79    85.4  879.28
   104.4  872.08   113.9  867.14   123.4  861.07   161.4  832.38   170.9   825.9
   189.9  815.16   218.3  801.46   247.4  783.65   286.1  758.64   305.4  747.22
   324.8  737.05   363.5  719.44   373.2   715.9   382.8   713.8   392.5  712.65
   402.2   712.1   421.6  713.09   489.3  717.88   508.6  718.63   518.3  719.46
     528  722.12   537.7  727.06   605.4  767.09   673.2   803.2   721.5  832.39
#Mann= 3 , 0 , 0
       0      .1       0   392.5    .045       0   421.6     .08       0
Bank Sta=392.5,421.6
XS Rating Curve= 0 ,0
Exp/Cntr=0.3,0.1

Type RM Length L Ch R = 1 ,9154.7  ,390,366.6,342.2
XS GIS Cut Line= 4
     1505225.485      253629.628      1505303.61        253883.1
     1505270.624      254185.184      1505326.18      254421.295
#Sta/Elev= 30
       0  905.17    68.8  886.13   108.1  873.39   127.7  864.89   147.4  855.24
     167   844.3   196.5  826.71   245.6  795.11   255.4  789.11   265.2  783.57
   314.2  757.88   343.7  740.98   353.5   736.1   382.9  723.71   402.5  714.52
   407.3713.0537   412.3  711.52   422.1  710.84   427.3711.1925   451.5  713.17
   539.7  716.08   598.2  717.64   607.9  719.38   617.6   723.3   627.3  728.31
   646.7  738.92   666.1   750.1   685.6  761.77   763.2  809.68   811.7  838.52
#Mann= 3 , 0 , 0
       0      .1       0   407.3    .045       0   427.3     .08       0
Bank Sta=407.3,427.3
XS Rating Curve= 0 ,0
Exp/Cntr=0.3,0.1

Type RM Length L Ch R = 1 ,8788.2  ,221.7,213.7,205.8
XS GIS Cut Line= 4
     1504730.694       253976.85     1504921.689      254122.192
     1505117.002      254297.973     1505251.116      254481.567
#Sta/Elev= 30
       0  893.04     9.6  891.58    19.2  888.52    28.8  883.98    57.6  868.61
   115.2  839.39   124.8  833.94     144  820.86   182.4   792.9   230.4  761.06
   249.7  746.29   288.7  713.65   298.4  707.89   300.5707.4929   308.1  706.06
   317.9  706.88   320.5707.4547   327.6  709.03   337.3   710.4   454.1  712.81
   483.3  716.12     493   716.8   502.8  718.34   512.2  722.18   531.2  733.04
   635.4  796.45   673.3  821.46   692.2  833.43   711.2  844.47   730.1   854.3
#Mann= 3 , 0 , 0
       0      .1       0   300.5    .045       0   320.5     .08       0
Bank Sta=300.5,320.5
XS Rating Curve= 0 ,0
Exp/Cntr=0.3,0.1

Type RM Length L Ch R = 1 ,8574.5  ,31,34.2,37.4
XS GIS Cut Line= 4
     1504706.674      254000.428     1504848.118      254340.145
     1505005.825      254409.959     1505108.147      254565.956
#Sta/Elev= 30
       0   886.7     9.7  882.34    38.7  866.01    77.5   847.4    87.2  841.52
   125.9   814.5   203.4  762.73     213  757.95   251.8  743.66   261.5  738.45
   280.8  724.58   290.5  718.92   300.2  715.79   309.9   714.3   348.6  712.47
   387.2   712.5   406.3  710.92   415.9  708.75   425.5  706.31   435.1  706.19
   441.2707.8152   454.2  711.65   463.8  713.02   511.7  715.41   521.3  717.92
   530.9  722.01   540.5  726.98   658.3  802.38   697.6   824.8     727  839.25
#Mann= 3 , 0 , 0
       0     .08       0   415.9    .045       0   441.2     .08       0
Bank Sta=415.9,441.2
XS Rating Curve= 0 ,0
Exp/Cntr=0.3,0.1

Type RM Length L Ch R = 1 ,8540.2  ,180.4,208.7,237
XS GIS Cut Line= 4
     1504700.782      254006.212     1504849.141      254370.463
     1504971.537      254444.248     1505040.982      254592.251
#Sta/Elev= 30
       0  884.48     9.8  879.95    39.3  862.91    68.8  849.26    78.7  843.61
   127.8  808.61   137.7  802.19   167.2  785.35   196.6   764.5   216.3  753.89
   245.8  743.27   255.6   737.8   265.5   731.4   275.3   724.2   285.2  718.61
     295  715.44   314.6     713   412.4  711.34   421.9  710.04   431.4  707.39
   440.9  705.16   450.5  706.04   469.5  712.65     479  714.32   498.1  715.31
   507.6  717.23   517.2  721.57   536.2  732.48   603.5  777.25   699.7  835.68
#Mann= 3 , 0 , 0
       0     .08       0   431.4    .045       0   450.5     .08       0
Bank Sta=431.4,450.5
XS Rating Curve= 0 ,0
Exp/Cntr=0.3,0.1

Type RM Length L Ch R = 1 ,8331.5  ,434.5,452.6,470.6
XS GIS Cut Line= 3
     1504675.138      254023.725     1504711.596      254329.281
     1504668.194      254770.253
#Sta/Elev= 30
       0  874.18    48.1  848.35    57.7  841.48    76.9  826.08   115.4     799
   134.6  786.44   153.9   775.1   201.9  748.67   230.8  731.04   240.4  726.97
     250  723.72   269.3  715.57   278.9   713.3   365.5  707.05   417.4702.5756
   423.3  702.17     433  702.39  436.53703.1597   442.6  704.49   461.8  711.64
   481.1  714.53   490.7  718.03   500.4  723.87   577.4  777.65   625.6  808.52
   635.2  813.84   644.9  818.31   654.5  821.45   664.1  822.83   750.8  825.65
#Mann= 3 , 0 , 0
       0     .08       0   417.4    .045       0  436.53     .08       0
Bank Sta=417.4,436.53
XS Rating Curve= 0 ,0
Exp/Cntr=0.3,0.1

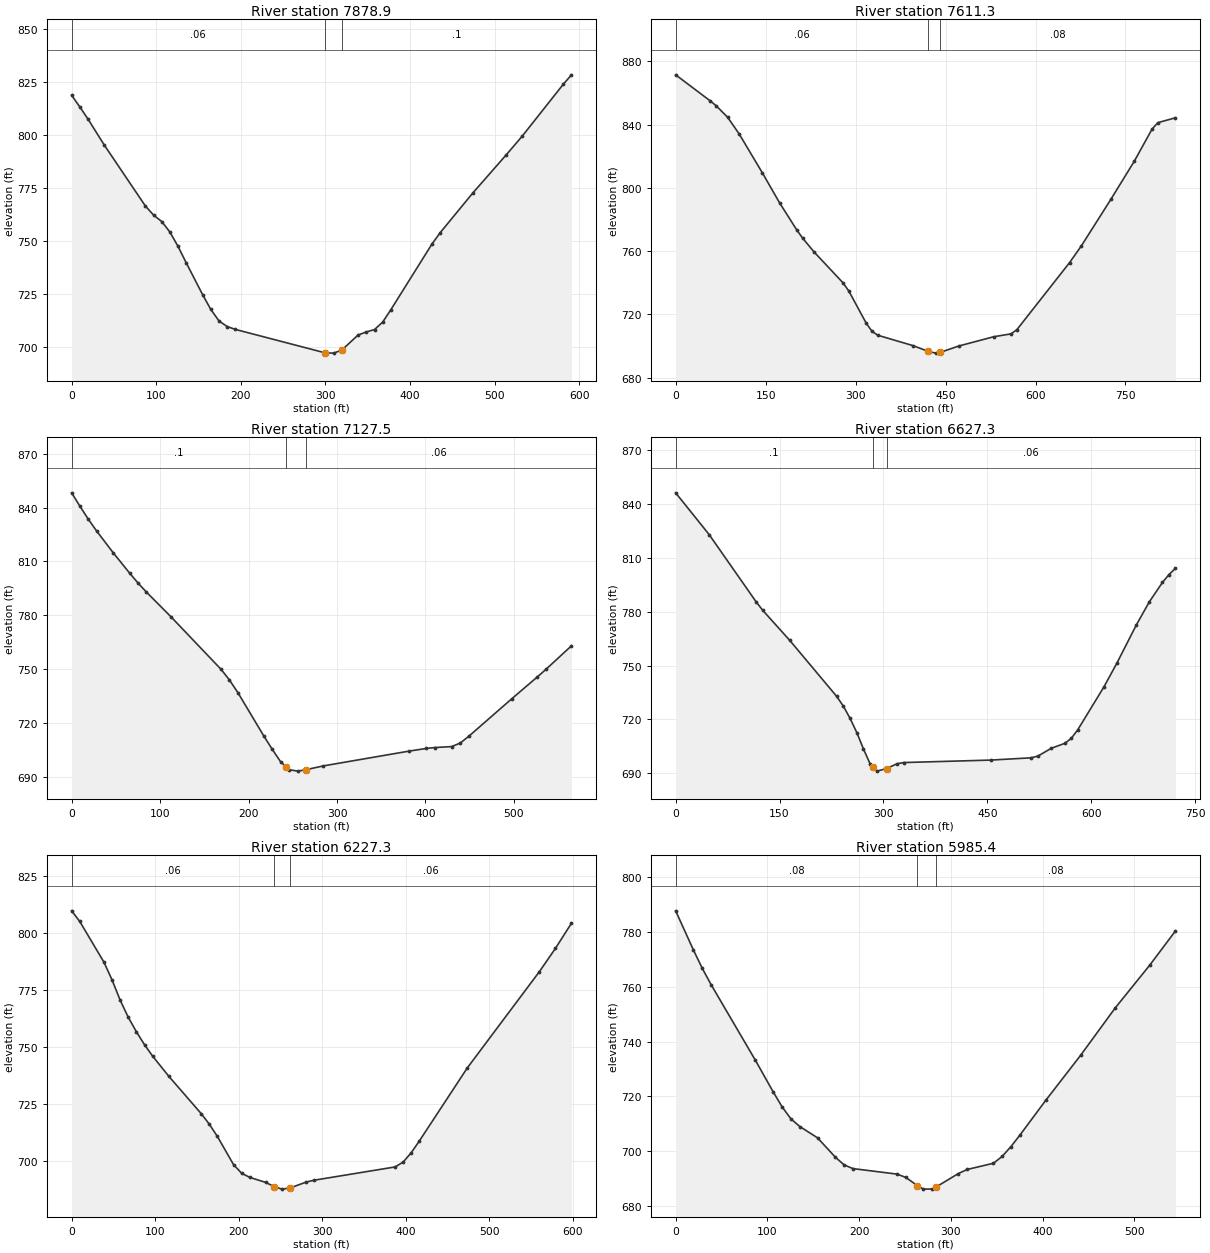
Type RM Length L Ch R = 1 ,7878.9  ,276.8,267.6,258.2
XS GIS Cut Line= 3
     1504548.402      254051.503     1504253.263      254331.017
      1504147.36      254482.059
#Sta/Elev= 30
       0   818.8     9.7   813.3    19.4  807.51    38.7  795.22    87.1  766.54
    96.8  762.22   106.5  759.17   116.1  754.23   125.8  747.39   135.5  739.63
   154.8  724.64   164.5  717.65   174.2   712.2   183.9  709.54   193.6  708.19
   299.4697.1563   309.7  696.99   319.4  698.42   338.7  705.56   348.4  706.99
   358.1  708.13   367.8  711.68   377.5  717.56   425.9  748.46   435.6  753.82
   474.4  772.69   513.3  790.41   532.7  799.48   581.2  823.97     591  828.47
#Mann= 3 , 0 , 0
       0     .06       0   299.4    .045       0   319.4      .1       0
Bank Sta=299.4,319.4
XS Rating Curve= 0 ,0
Exp/Cntr=0.3,0.1

Type RM Length L Ch R = 1 ,7611.3  ,498.8,483.8,467.7
XS GIS Cut Line= 4
     1504248.055       253664.35      1504209.86      253921.295
     1504060.555      254235.531     1504020.624      254457.753
#Sta/Elev= 30
       0  871.56    57.7  855.06    67.4  852.05    86.6  844.74   105.8  834.23
   144.3  809.74   173.2  790.64     202   773.4   211.7  768.27   230.9  759.48
   279.1  739.98   288.8  734.76   317.8  714.43   327.4  709.35   337.1  706.84
   395.1  700.36   421.4696.6364   433.7  695.54   441.4696.0623   472.4  700.08
   530.4  705.91   559.4  707.74     569  710.41   656.8   752.8   676.4  763.35
   725.5  792.73   764.7  816.92   794.2  837.16     804  841.31   833.4   844.4
#Mann= 3 , 0 , 0
       0     .06       0   421.4    .045       0   441.4     .08       0
Bank Sta=421.4,441.4
XS Rating Curve= 0 ,0
Exp/Cntr=0.3,0.1

Type RM Length L Ch R = 1 ,7127.5  ,496.8,500.2,503.6
XS GIS Cut Line= 3
     1503649.096      253827.545      1503669.93      254004.628
      1503741.11      254384.836
#Sta/Elev= 30
       0   848.2     9.4  840.71    18.8  833.53    28.2  826.98    46.9   814.9
    65.7  803.44    75.1  797.96    84.5  792.99   112.6  779.07   168.9     750
   178.3  744.14     188  736.99     217  713.11   226.7  705.55   236.3  698.53
   242.2695.8539     246  694.13   255.7  693.36   265.3   694.2   284.7  696.28
   381.4  704.49   400.7  705.96   410.4  706.47   429.7  707.03   439.4     709
   449.1  712.81   497.4  733.54   526.4  745.74   536.1  749.93   565.1   763.1
#Mann= 3 , 0 , 0
       0      .1       0   242.2    .045       0   265.3     .06       0
Bank Sta=242.2,265.3
XS Rating Curve= 0 ,0
Exp/Cntr=0.3,0.1

Type RM Length L Ch R = 1 ,6627.3  ,398.8,400,400.6
XS GIS Cut Line= 3
     1503179.502      253812.296     1503205.543      254373.494
     1503242.846      254528.934
#Sta/Elev= 30
       0  846.26    48.4  822.96   116.2   785.5   125.9   780.7   164.7  764.04
   232.5   732.8   242.2  727.31   251.8  720.56   261.5  712.67   271.2  703.45
   280.9  695.06   284.5693.6023   290.6  691.14   304.5692.5375   319.6  695.26
   329.3  695.92   455.2   697.3   513.4  698.57   523.1  699.54   542.4  703.88
   561.8  706.62   571.2  709.38   580.6  714.19   618.2  737.99     637  751.27
   665.2  772.64     684  785.55   702.8  796.28   712.2  800.68   721.7  804.22
#Mann= 3 , 0 , 0
       0      .1       0   284.5    .045       0   304.5     .06       0
Bank Sta=284.5,304.5
XS Rating Curve= 0 ,0
Exp/Cntr=0.3,0.1

Type RM Length L Ch R = 1 ,6227.3  ,239.9,241.9,244
XS GIS Cut Line= 3
     1502801.874       253936.92     1502805.346      254304.975
     1502739.374      254525.461
#Sta/Elev= 30
       0  809.85     9.7  805.18    38.7  787.26    48.4  779.45    58.1  770.57
    67.8  763.06    77.5  756.73    87.2  751.04    96.9  746.03   116.2  737.21
     155   720.8   164.7  716.17   174.4  710.75   193.7  698.42   203.4  694.59
   213.1  692.79   232.5  690.54   242.2  688.74   251.8  687.62   261.5  688.13
   280.9  690.75   290.6  691.56   387.2  697.37   396.8  699.52   406.4  703.62
     416  708.71   473.6  740.91   559.9   783.2     579  793.36   598.2  804.42
#Mann= 3 , 0 , 0
       0     .06       0   242.2    .045       0   261.5     .06       0
Bank Sta=242.2,261.5
XS Rating Curve= 0 ,0
Exp/Cntr=0.3,0.1

Type RM Length L Ch R = 1 ,5985.4  ,36.1,35.7,35.3
XS GIS Cut Line= 4
     1502673.402      253909.142     1502570.848      254084.273
     1502556.607      254284.525     1502473.749      254398.725
#Sta/Elev= 30
       0  787.57    19.3  773.36      29  766.64    38.7  760.66      87  733.12
   106.3  721.67     116  716.23   125.6  711.86   135.3  709.06   154.6  704.95
     174  697.92   183.6  695.09   193.3  693.74   241.2  691.74   250.8  690.55
   263.3687.5754   269.9  686.27   279.4  686.32   283.3686.9363   308.1  691.93
   317.7  693.42   346.4  695.69   355.9  698.18   365.5  701.78     375  705.84
   403.7  718.73   441.3  734.94     479  752.18   516.6  767.74   544.8  780.27
#Mann= 3 , 0 , 0
       0     .08       0   263.3    .045       0   283.3     .08       0
Bank Sta=263.3,283.3
XS Rating Curve= 0 ,0
Exp/Cntr=0.3,0.1

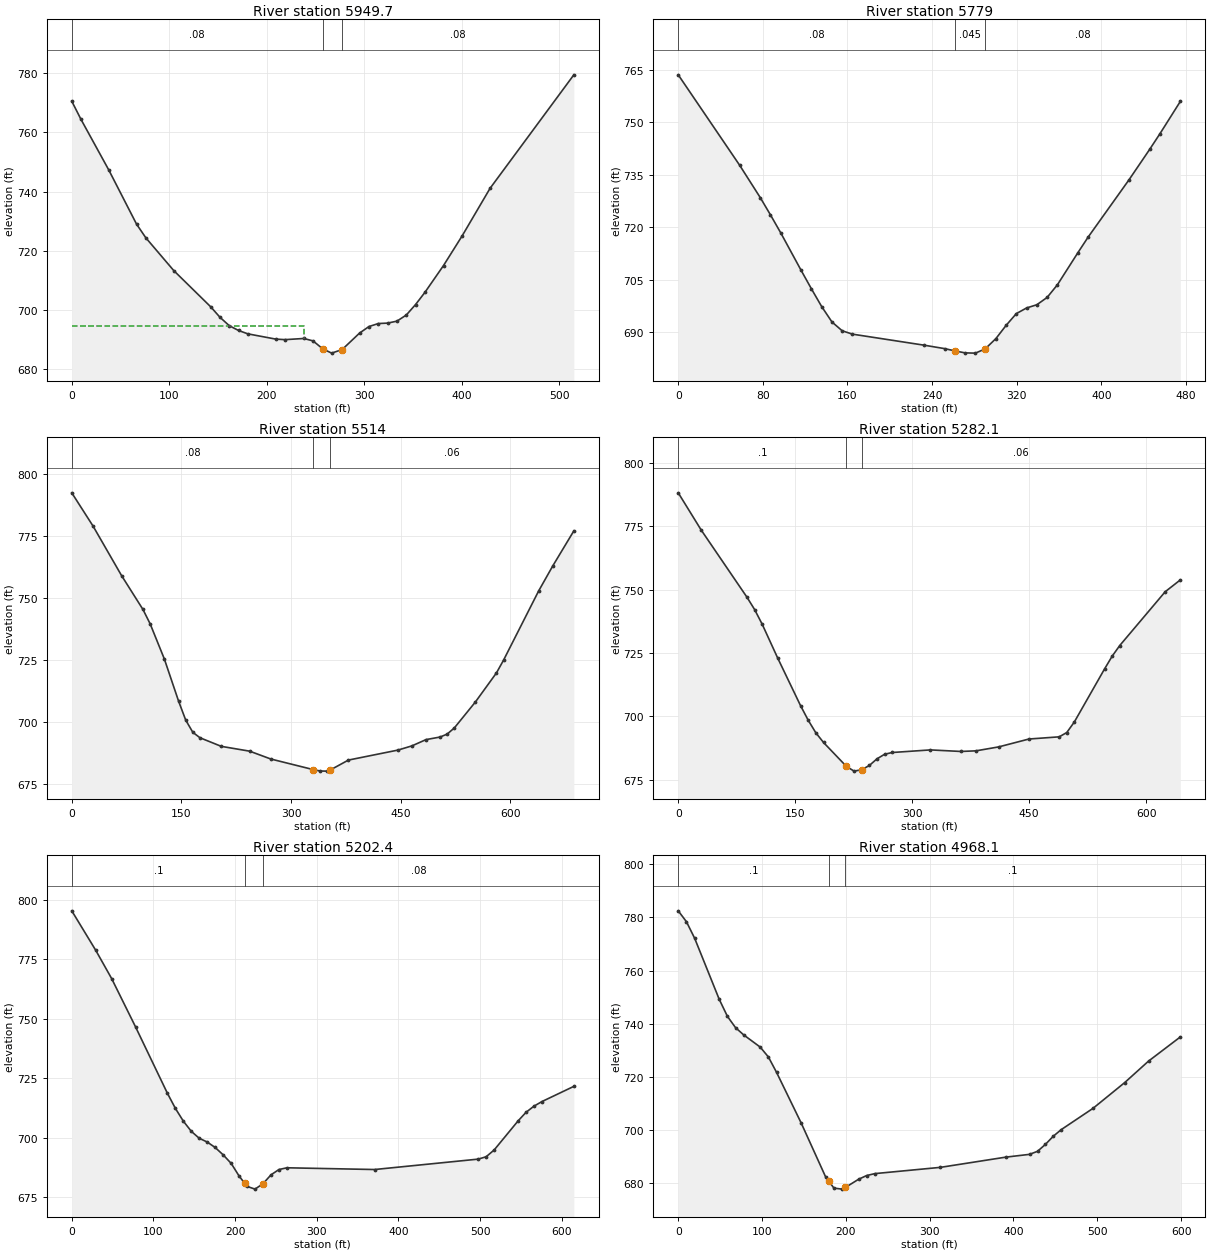
Type RM Length L Ch R = 1 ,5949.7  ,158.7,170.7,182.5
XS GIS Cut Line= 4
     1502626.919      253911.261     1502534.905      254066.643
     1502524.489      254257.616     1502438.551      254372.199
#Sta/Elev= 30
       0  770.57     9.5   764.4      38   747.3    66.5  728.99      76  724.38
   104.6  713.32   142.6  701.04   152.1   697.5   161.6  694.67   171.1  693.06
   180.6  691.92   209.3  690.14   218.8  689.96     238  690.35   247.5  689.54
   257.4686.8718   266.6   685.4   277.4  686.61   295.3  692.19   304.9  694.39
   314.5   695.4     324  695.55   333.6  696.21   343.2  698.28   352.7  701.82
   362.3  705.94   381.4  715.02   400.5  725.04   429.1   741.1   515.1  779.49
#Mann= 3 , 0 , 0
       0     .08       0   257.4    .045       0   277.4     .08       0
#XS Ineff= 2 , 0
          238.09  694.65
Permanent Ineff=
       F       F
Bank Sta=257.4,277.4
XS Rating Curve= 0 ,0
Exp/Cntr=0.3,0.1

Type RM Length L Ch R = 1 ,5779    ,262.4,265,267.1
XS GIS Cut Line= 2
     1502510.208      253867.475     1502270.624      254277.197
#Sta/Elev= 30
       0  763.58    58.1  737.68    77.5  728.46    87.2  723.49    96.9  718.35
   116.2   707.6   125.9  702.33   135.6  697.25   145.3  692.85     155  690.32
   164.7  689.36   232.5   686.2   251.8  685.22   261.5  684.57   271.2     684
   280.9  683.93   290.1 685.135   300.3   688.1     310   691.9   319.6  695.24
   329.3  696.86     339  697.78   348.7  699.87   358.4  703.48   377.8  712.68
   387.4  717.11   426.2  733.58   445.6  742.23   455.3   746.7   474.6  755.96
#Mann= 3 , 0 , 0
       0     .08       0   261.5    .045       0   290.1     .08       0
Bank Sta=261.5,290.1
XS Rating Curve= 0 ,0
Exp/Cntr=0.3,0.1

Type RM Length L Ch R = 1 ,5514    ,238.9,231.9,224.8
XS GIS Cut Line= 4
     1502260.208      253662.614     1502211.596      253881.364
     1502048.402      254108.795     1501996.319      254284.142
#Sta/Elev= 30
       0  792.41    29.2  778.95    68.2  758.98    97.4  745.35   107.2  739.58
   126.7  725.35   146.1   708.4   155.9  700.72   165.6  695.81   175.4   693.6
   204.6  690.13   243.4  688.19   272.4  685.02   330.3  680.76   339.9  680.18
   349.6  680.14  353.86680.6349   378.5   684.6   446.1  688.62   465.4  690.33
   484.7  692.86     504   693.9   513.6  695.09   523.3  697.53   552.2  708.03
     581  719.76   590.7  724.89   638.8  752.86     658  762.89   686.9  777.06
#Mann= 3 , 0 , 0
       0     .08       0   330.3    .045       0  353.86     .06       0
Bank Sta=330.3,353.86
XS Rating Curve= 0 ,0
Exp/Cntr=0.3,0.1

Type RM Length L Ch R = 1 ,5282.1  ,81.9,79.7,77.5
XS GIS Cut Line= 3
     1502043.194      253617.475     1501932.083      253931.711
     1501876.527      254237.267
#Sta/Elev= 30
       0  788.11    29.4  773.47    88.2  746.96      98   742.1   107.8  736.26
   127.4  723.12   156.8  704.31   166.6  698.57   176.4   693.6   186.3  689.77
   215.6680.3546   225.5  678.47   235.3  679.02   245.1   680.7   254.9  683.32
   264.7  685.12   274.5  685.81   323.5  686.83   362.4  686.22   381.8  686.46
   410.9  688.01   449.8  691.12   488.6  691.98   498.3  693.68     508  697.84
   546.8  718.76   556.5  723.75   566.2  727.94   624.5  749.14   643.9   753.8
#Mann= 3 , 0 , 0
       0      .1       0   215.6    .045       0   235.3     .06       0
Bank Sta=215.6,235.3
XS Rating Curve= 0 ,0
Exp/Cntr=0.3,0.1

Type RM Length L Ch R = 1 ,5202.4  ,252.8,234.3,215.7
XS GIS Cut Line= 2
     1501947.708      253589.697      1501794.93      254185.184
#Sta/Elev= 30
       0  795.36    29.3  778.82    48.8  766.93    78.1  746.63   117.1  718.76
   126.9   712.4   136.6  707.06   146.4  702.77   156.1  699.86   165.9  698.28
   175.6  695.99   185.4   692.9   195.2  689.31   204.9  684.01   211.9680.8932
   214.7  679.65   224.4  678.51   234.2   680.8     244  684.52   253.7  686.74
   263.5  687.47   370.8  686.74   497.7  691.11   507.4   692.1   517.2  694.94
   546.5  707.15   556.2  710.75     566  713.35   575.7  715.27   614.8  721.66
#Mann= 3 , 0 , 0
       0      .1       0   211.9    .045       0   234.2     .08       0
Bank Sta=211.9,234.2
XS Rating Curve= 0 ,0
Exp/Cntr=0.3,0.1

Type RM Length L Ch R = 1 ,4968.1  ,213,222.2,231.1
XS GIS Cut Line= 3
      1501584.86      253693.864      1501763.68       254030.67
     1501796.666      254245.947
#Sta/Elev= 30
       0   782.5     9.8   778.4    19.6  772.17    48.9  749.22    58.7   742.8
    68.4  738.55    78.2  735.81    97.8  731.25   107.6  727.52   117.3  721.76
   146.7   702.7     176  682.33   179.4680.8951   185.8   678.2   195.6  677.82
   199.4678.4407   215.1  681.51   224.9  682.94   234.7  683.66   312.9  686.01
   390.8  689.85   419.2   690.9   428.7  692.04   438.2  694.67   447.6  697.74
   457.1  700.22     495  708.22   532.8  717.91   561.2  725.98   599.1  735.06
#Mann= 3 , 0 , 0
       0      .1       0   179.4    .045       0   199.4      .1       0
Bank Sta=179.4,199.4
XS Rating Curve= 0 ,0
Exp/Cntr=0.3,0.1

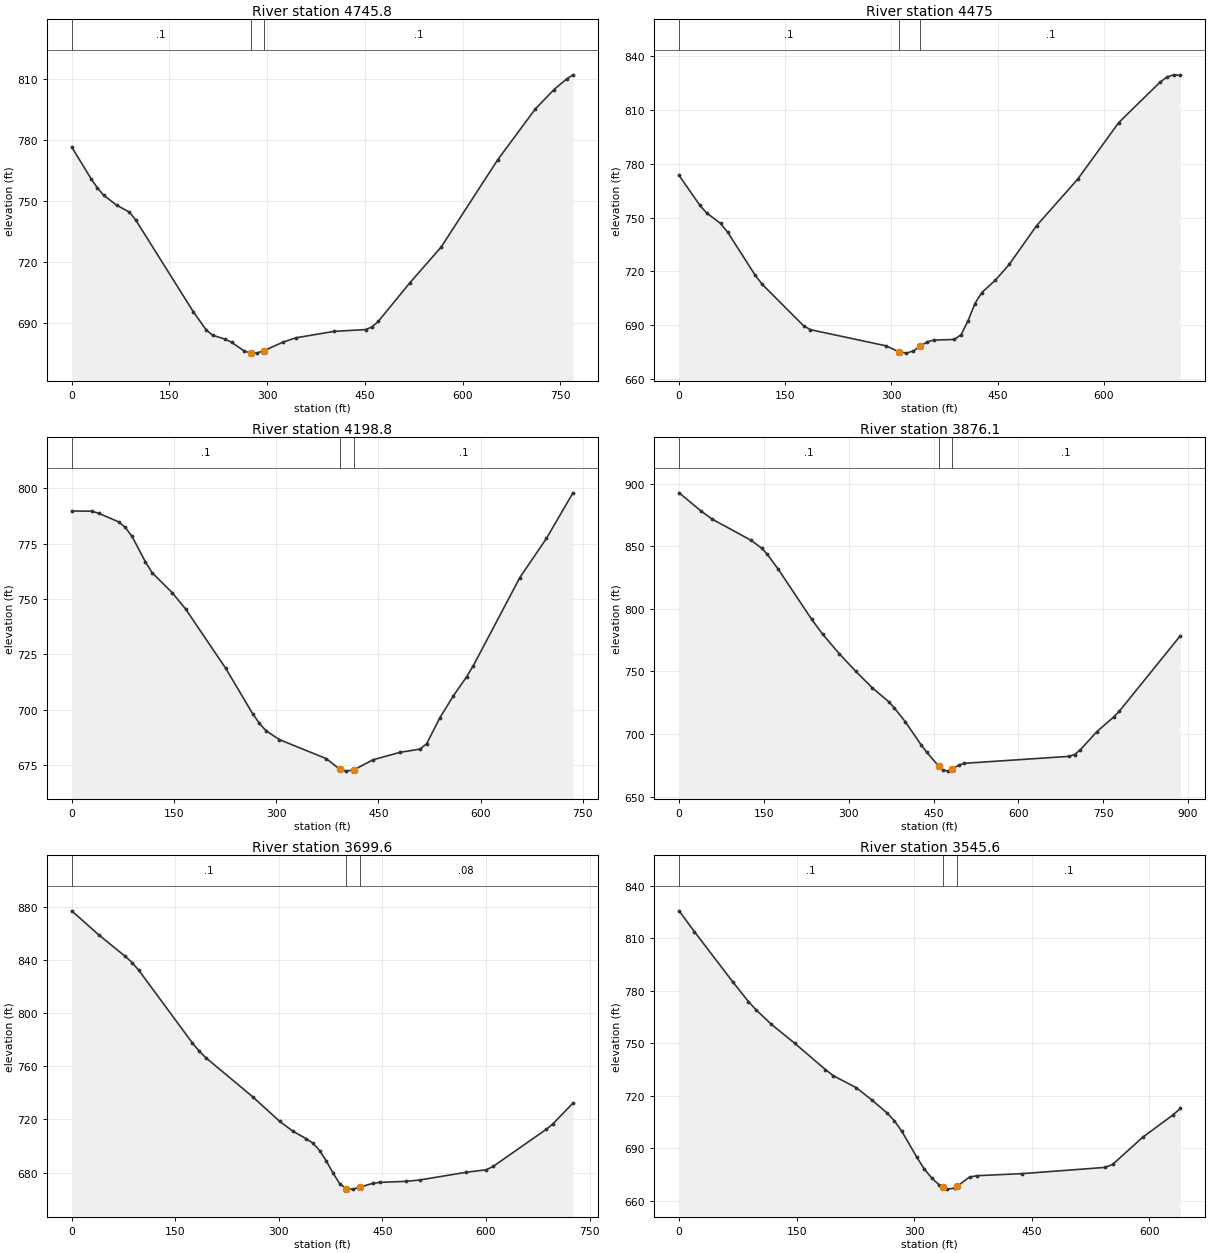
Type RM Length L Ch R = 1 ,4745.8  ,235.9,270.8,305.6
XS GIS Cut Line= 4
     1501534.513      253706.017     1501475.485        253883.1
     1501504.999      254107.059     1501329.652      254417.822
#Sta/Elev= 30
       0  776.41    29.5  760.93    39.3  756.37    49.1   752.7    68.8  747.87
    88.4  744.46    98.2  740.58   186.7  695.48   206.3  686.64   216.1     684
   235.8  682.02   245.6  680.47   265.2  676.17   274.6675.2395   275.1  675.19
   284.9  675.32   294.6676.3096   324.2  680.58   343.8  682.69   402.7  685.88
   451.1  686.75   460.8  688.05   470.4  690.72   518.6  709.57   566.9   727.2
   653.6  770.01   711.5  795.05   740.4  804.63   759.7  809.83   769.4  811.84
#Mann= 3 , 0 , 0
       0      .1       0   274.6    .045       0   294.6      .1       0
Bank Sta=274.6,294.6
XS Rating Curve= 0 ,0
Exp/Cntr=0.3,0.1

Type RM Length L Ch R = 1 ,4475    ,275.2,276.2,277.7
XS GIS Cut Line= 3
     1501518.888      253707.753     1501364.374      253857.059
     1500895.624      254011.572
#Sta/Elev= 30
       0  773.51    29.3  756.85    39.1  752.52    58.6  746.71    68.4  741.98
   107.4   717.9   117.2  712.86   175.8  689.64   185.6  687.43   292.3  678.43
   310.6675.0737   321.3  674.34     331  675.55   340.7  678.17   350.4  680.59
     360   681.6   389.1  681.97   398.7  684.72   408.4  692.49   418.1  702.01
   427.8  708.16   447.1   715.1   466.5  723.84   505.2  745.47   563.3  771.42
   621.3     803   679.4  825.46   689.1  828.31   698.8  829.66   708.4  829.32
#Mann= 3 , 0 , 0
       0      .1       0   310.6    .045       0   340.7      .1       0
Bank Sta=310.6,340.7
XS Rating Curve= 0 ,0
Exp/Cntr=0.3,0.1

Type RM Length L Ch R = 1 ,4198.8  ,354,322.7,290.4
XS GIS Cut Line= 4
      1501616.11      253646.989     1501336.596      253591.434
     1501079.652      253657.406     1500985.902      253817.128
#Sta/Elev= 30
       0  789.76    29.5  789.67    39.3  788.77    68.8  784.86    78.6  782.36
    88.4  778.33   108.1  766.79   117.9   761.9   147.4  752.84   167.1  745.46
     226  718.62   265.3   698.2   275.2  693.86     285  690.44   304.6  686.43
   373.4  677.82   393.1  673.07   402.9  672.16   413.9672.7233   442.2   677.3
   481.5  680.65     511  682.11   520.8  684.56   540.4   696.4     560  706.21
   579.5  714.85   589.2  719.81   657.5  759.65   696.5  777.34   735.5  797.98
#Mann= 3 , 0 , 0
       0      .1       0   393.1    .045       0   413.9      .1       0
Bank Sta=393.1,413.9
XS Rating Curve= 0 ,0
Exp/Cntr=0.3,0.1

Type RM Length L Ch R = 1 ,3876.1  ,178.3,176.5,174.3
XS GIS Cut Line= 4
     1501123.055      252910.878     1501090.069      253299.767
     1501081.388      253461.225      1500982.43       253780.67
#Sta/Elev= 30
       0  892.56      39  877.95    58.5  871.54   126.8  854.79   146.4  848.27
   156.1  843.39   175.6  831.43   234.2  791.74   253.7   779.8     283  764.28
   312.2  750.16   341.5  736.99   370.8  725.76   380.5  720.95   399.8  709.96
   428.3   691.2   437.8  685.57  459.14674.4136   466.4   671.3   475.9  670.43
  482.27671.8314   494.9   675.3   504.4  676.66   689.7  682.23   699.5  683.67
   709.4  687.46   738.9  701.97   768.4  713.62   778.2  718.11   886.4   778.5
#Mann= 3 , 0 , 0
       0      .1       0  459.14    .045       0  482.27      .1       0
Bank Sta=459.14,482.27
XS Rating Curve= 0 ,0
Exp/Cntr=0.3,0.1

Type RM Length L Ch R = 1 ,3699.6  ,160,153.9,147.6
XS GIS Cut Line= 3
     1500963.369      252984.511     1500908.681      253310.032
     1500919.098      253705.865
#Sta/Elev= 30
       0  877.37    38.8  859.42    77.7  842.95    87.4  838.39    97.1  832.57
   174.8   777.7   184.5  771.64   194.2  766.62   262.1  737.14     301  718.68
   320.4  711.17   339.7   705.5   349.4  702.13   359.1  696.58   368.7  688.74
   378.4  679.69     388  671.69   397.7  667.72   407.4  667.49     417  668.96
   436.3   671.9     446  672.55   484.6  673.39   503.9  674.37   571.5  680.23
   600.5  682.09   610.2  684.56   687.4  712.61   697.1  716.76     726  732.39
#Mann= 3 , 0 , 0
       0      .1       0   397.7    .045       0     417     .08       0
Bank Sta=397.7,417
XS Rating Curve= 0 ,0
Exp/Cntr=0.3,0.1

Type RM Length L Ch R = 1 ,3545.6  ,361.5,356,349.6
XS GIS Cut Line= 3
     1500555.346      253143.517     1500735.902      253324.072
     1500840.069      253693.864
#Sta/Elev= 30
       0  825.61    19.6  813.68    68.8  784.83    88.4  773.81    98.2  769.05
   117.8  760.77   147.3  750.05   186.6  734.97   196.4  731.52   225.9  724.63
   245.5  717.73     265  710.29   274.6  705.74   284.2  699.63   303.4  684.78
     313  678.05   322.6  672.88   332.2  668.91   336.9667.8084   341.8  666.66
   351.4  667.22  355.15668.4462   370.6  673.58   380.2  674.33   437.8  675.52
   543.5  679.07   553.1  680.78   591.5  696.29   629.9  708.98   639.5  712.74
#Mann= 3 , 0 , 0
       0      .1       0   336.9    .045       0  355.15      .1       0
Bank Sta=336.9,355.15
XS Rating Curve= 0 ,0
Exp/Cntr=0.3,0.1