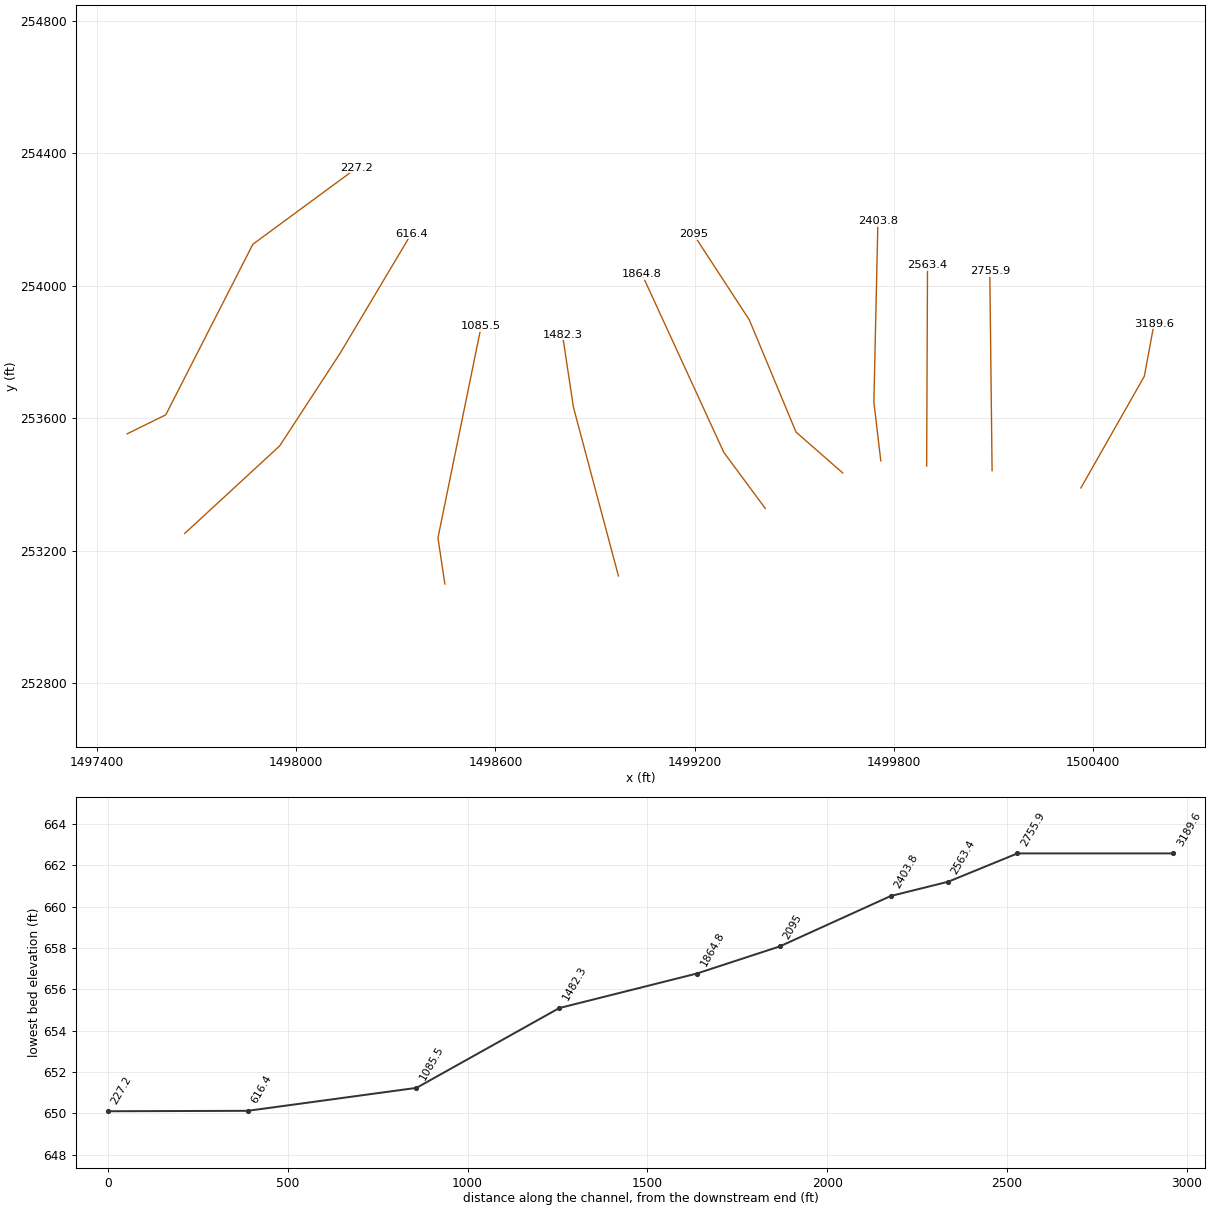
HEC-RAS study ADDSRN.prj: ADDSRN

--- ADDSRN.g01 (geometry) --- (continued)

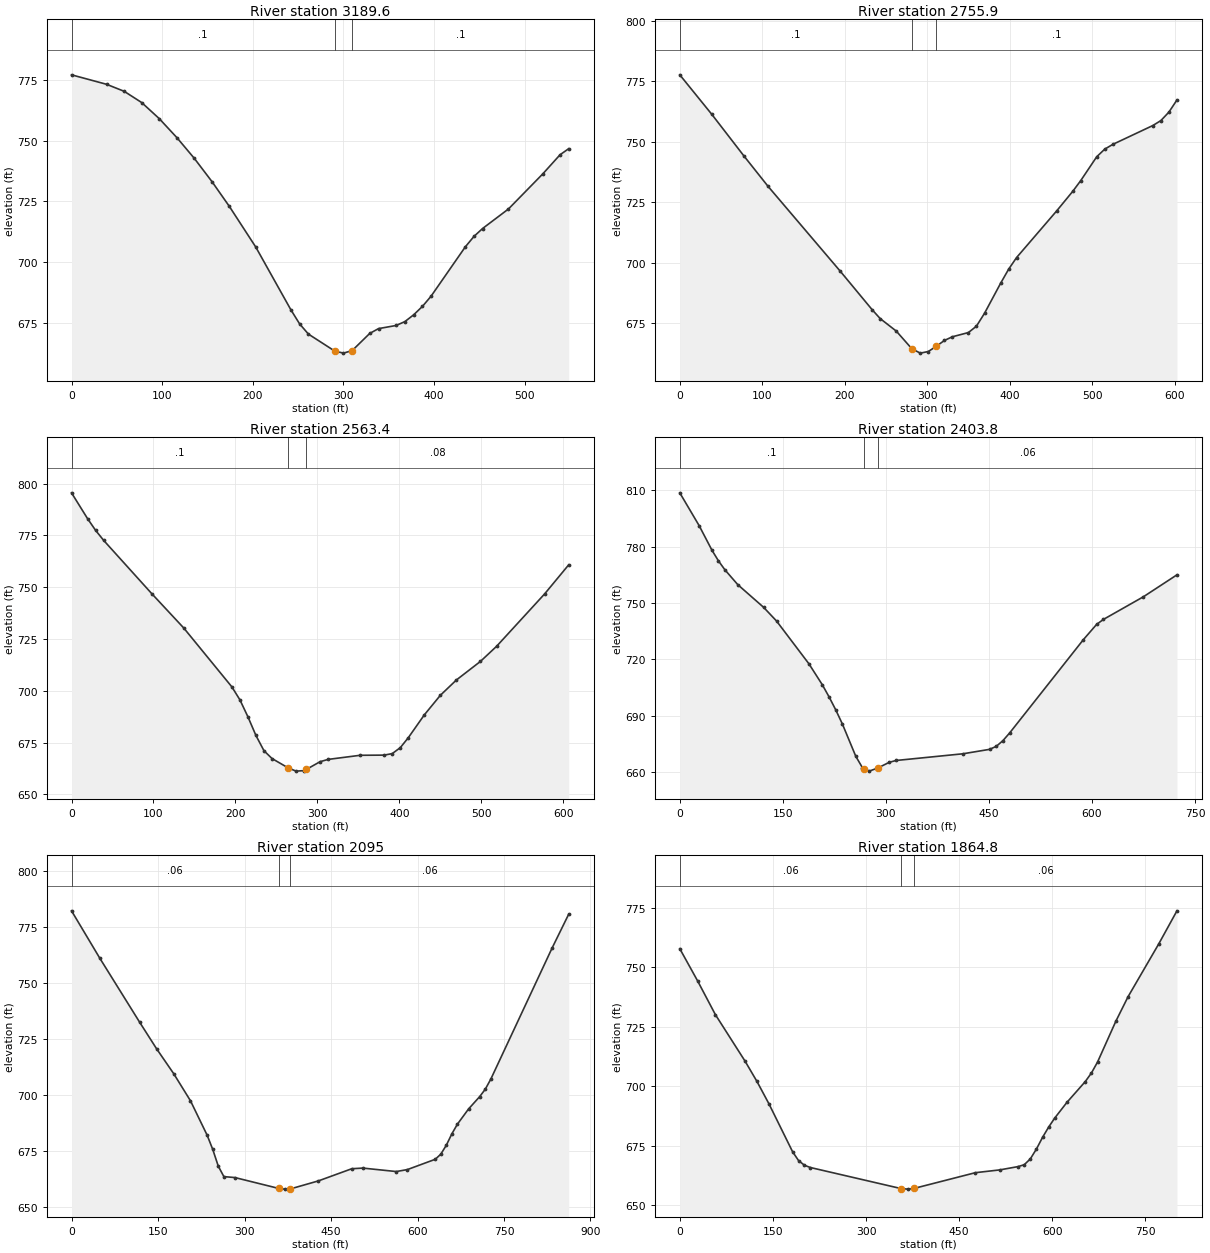
Type RM Length L Ch R = 1 ,3189.6  ,420.2,433.7,446.7
XS GIS Cut Line= 3
     1500362.638      253390.045      1500553.61       253726.85
      1500582.95      253885.572
#Sta/Elev= 30
       0  777.06    38.7  773.16    58.1  770.28    77.4  765.66    96.8  759.04
   116.2  751.25   135.5  742.69   154.9  733.17   174.2  722.91   203.3  706.21
     242  680.43   251.7  674.59   261.4   670.4   290.4  663.43   300.1  662.57
   309.7  663.62   329.1  670.69   338.8  672.66   358.1  673.94   367.8  675.53
   377.5  678.32   387.2  681.79   396.7  685.97   434.6  706.32   444.2  710.63
   453.6  713.84   482.1  721.86   520.1  736.34   539.1  744.19   548.6  746.67
#Mann= 3 , 0 , 0
       0      .1       0   290.4    .045       0   309.7      .1       0
Bank Sta=290.4,309.7
XS Rating Curve= 0 ,0
Exp/Cntr=0.3,0.1

Type RM Length L Ch R = 1 ,2755.9  ,192.9,192.5,192.1
XS GIS Cut Line= 2
     1500095.277      253442.128     1500088.333      254044.559
#Sta/Elev= 30
       0  777.64    38.9  761.26    77.7  744.11   106.9  731.56   194.4  696.47
   233.2  680.49   242.9  676.84   262.4  671.67   281.3664.3464   291.5  662.57
   301.2  663.24     311  665.43   320.7  667.81   330.4  669.34   349.8  671.08
   359.5  673.72   369.3  679.04   388.7  691.39   398.4   697.2   408.1  702.07
   456.7  721.36   476.2  729.46   485.9   733.9   505.3  743.78     515  746.91
   524.7  748.87   573.3  756.68     583  758.72   592.8  762.24   602.5  767.25
#Mann= 3 , 0 , 0
       0      .1       0   281.3    .045       0     311      .1       0
Bank Sta=281.3,311
XS Rating Curve= 0 ,0
Exp/Cntr=0.3,0.1

Type RM Length L Ch R = 1 ,2563.4  ,159.9,159.6,159
XS GIS Cut Line= 2
     1499898.265      253455.865     1499900.869      254062.636
#Sta/Elev= 30
       0  795.55    19.6  783.07    29.4  777.43    39.2  772.61    97.9  746.89
     137  730.28   195.7  701.87   205.5  695.63   215.3  687.42   225.1   678.4
   234.9  671.04   244.7  667.28   264.2  662.81     274   661.2   283.8  661.44
   286.6662.0237   303.4  665.76   313.2  666.86   352.3  668.85   381.7  668.93
   391.5  669.67   401.3  672.55     411  677.31   430.6  688.36   450.2  697.82
   469.8  705.22   499.1  714.17   518.7  721.42   577.4  746.74   606.8  760.79
#Mann= 3 , 0 , 0
       0      .1       0   264.2    .045       0   286.6     .08       0
Bank Sta=264.2,286.6
XS Rating Curve= 0 ,0
Exp/Cntr=0.3,0.1

Type RM Length L Ch R = 1 ,2403.8  ,298.2,308.8,319.1
XS GIS Cut Line= 3
     1499760.208      253471.642     1499739.374      253648.725
     1499751.527      254193.864
#Sta/Elev= 30
       0  808.71    28.2  791.22    46.9   778.1    56.3  772.47    65.7   767.7
    84.5  759.78     122  747.74   140.8  740.46     188  717.64   207.5  706.47
   217.2   700.1     227  693.13   236.7  685.57   256.2  668.38   265.9   662.3
   268.2661.8783   275.7  660.51   288.2662.1805   304.9   665.2   314.6  666.17
     412  669.74   450.9  672.11   460.7  673.72   470.4  676.78   480.2  680.88
   587.3  730.48   606.7  738.66   616.5  741.28   674.9  753.39   723.6  765.04
#Mann= 3 , 0 , 0
       0      .1       0   268.2    .045       0   288.2     .06       0
Bank Sta=268.2,288.2
XS Rating Curve= 0 ,0
Exp/Cntr=0.3,0.1

Type RM Length L Ch R = 1 ,2095    ,229.2,230.2,231.1
XS GIS Cut Line= 4
     1499645.624      253435.184     1499504.999      253558.447
     1499364.374      253896.989     1499195.971       254155.67
#Sta/Elev= 30
       0   782.3    49.2  761.08   118.1  732.59   147.6  720.69   177.2  709.61
   206.3   697.5   235.2  682.14   244.9  675.81   254.5  668.33   264.2  663.66
   283.5  663.23   359.7658.3581   370.3  658.07   379.7658.1778   428.2  661.75
   486.1  667.18   505.4  667.46   563.2  665.92   582.5   666.8   630.8  671.39
   640.4  673.67     650  677.67   659.7   682.8   669.3   687.1   688.6  693.87
   707.9  699.38   717.6   702.7   727.2  707.21   833.3  765.63   862.2  780.78
#Mann= 3 , 0 , 0
       0     .06       0   359.7    .045       0   379.7     .06       0
Bank Sta=359.7,379.7
XS Rating Curve= 0 ,0
Exp/Cntr=0.3,0.1

Type RM Length L Ch R = 1 ,1864.8  ,386.7,382.5,378.2
XS GIS Cut Line= 3
     1499412.574      253327.921     1499287.574      253497.192
     1499041.494       254033.99
#Sta/Elev= 30
       0  757.79    28.7  744.26    57.4  730.06   105.2  710.52   124.3  702.02
   143.5  692.67   181.7  672.48   191.3  668.77   200.9  666.78   210.4  665.84
   357.1 656.954   367.9  656.76   377.1657.0426   476.2  663.67   515.5  664.84
     545  666.23   554.9  667.02   564.7  669.46   574.6  673.64   584.4  678.52
   594.3  682.86   604.1  686.66   623.8  693.26   653.3  701.98   663.2  705.59
     673  710.17   702.5  727.33   722.2  737.64   771.4  759.72   800.9   773.7
#Mann= 3 , 0 , 0
       0     .06       0   357.1    .045       0   377.1     .06       0
Bank Sta=357.1,377.1
XS Rating Curve= 0 ,0
Exp/Cntr=0.3,0.1

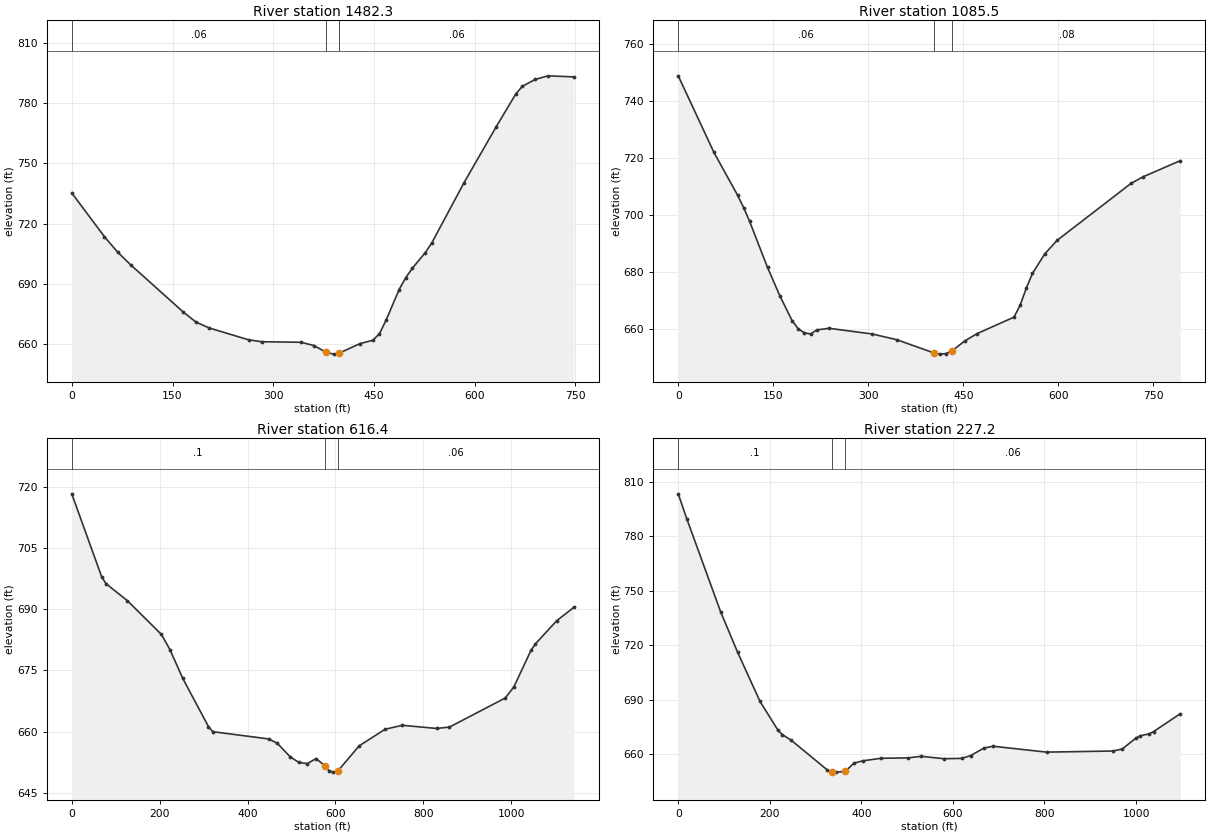
Type RM Length L Ch R = 1 ,1482.3  ,407.8,396.8,384.3
XS GIS Cut Line= 3
     1498970.277       253124.42      1498834.86        253633.1
     1498801.874       253851.85
#Sta/Elev= 30
       0  735.25    48.7  713.47    68.2  705.86    87.7   699.5   165.7  676.11
   185.2  670.96   204.7   668.1   263.2  662.22   282.7  661.26   341.2  660.99
   360.7  659.36   378.6655.9841   389.9  655.09   398.6655.6567   428.9  660.28
   448.4     662   458.2  665.28   467.9  671.86   487.4  687.18   497.2  693.06
   506.9  697.71   526.4  705.56     536  710.35   584.1  740.36   632.2  768.29
     661  784.38   670.7  788.22   689.9  791.69   709.2   793.5   747.6  792.97
#Mann= 3 , 0 , 0
       0     .06       0   378.6    .045       0   398.6     .06       0
Bank Sta=378.6,398.6
XS Rating Curve= 0 ,0
Exp/Cntr=0.3,0.1

Type RM Length L Ch R = 1 ,1085.5  ,479.1,469.1,459.4
XS GIS Cut Line= 3
     1498447.731      253100.056     1498426.897      253239.379
     1498557.083      253877.892
#Sta/Elev= 30
       0  748.87    56.4  721.98    93.9  706.89   103.3  702.61   112.7  697.78
   140.9  681.65   160.3  671.73   179.8  662.96   189.5  660.09   199.2   658.7
     209   658.3   218.7  659.72   238.1  660.29   306.2   658.3   345.1  656.28
   403.5  651.65   413.2  651.23   422.9  651.44   432.7  652.46   452.1  655.82
   471.6  658.41   529.9   664.2   539.6  668.34   549.4  674.38   559.1  679.52
   578.6  686.42     598  691.14   714.7  711.13   734.2  713.49   792.5  719.11
#Mann= 3 , 0 , 0
       0     .06       0   403.5    .045       0   432.7     .08       0
Bank Sta=403.5,432.7
XS Rating Curve= 0 ,0
Exp/Cntr=0.3,0.1

Type RM Length L Ch R = 1 ,616.4   ,385.7,389.1,391.2
XS GIS Cut Line= 4
     1497664.721      253252.892     1497950.335      253516.723
     1498132.627      253796.671     1498347.013      254157.406
#Sta/Elev= 30
       0  718.24      68  697.94    77.8  696.26   126.4   692.1   204.1  683.82
   223.6  680.06   252.7  673.04   311.1  661.26   320.8  660.02   447.8  658.25
   467.4  657.21   496.9  653.88   516.6   652.5   536.2   652.2   555.8  653.44
   575.5  651.73   585.3  650.48   595.2  650.12   605.1650.3595   654.1  656.56
   713.1  660.62   752.2  661.58   830.2  660.81   859.5  661.15   986.4  668.26
  1005.9  670.96  1044.9  679.91  1054.7  681.47  1103.5  687.18  1142.5  690.45
#Mann= 3 , 0 , 0
       0      .1       0   575.5    .045       0   605.1     .06       0
Bank Sta=575.5,605.1
XS Rating Curve= 0 ,0
Exp/Cntr=0.3,0.1

Type RM Length L Ch R = 1 ,227.2   ,259.5,227.2,195.1
XS GIS Cut Line= 4
      1497491.11      253553.239      1497607.43      253610.531
     1497869.619      254125.136     1498183.124      254356.191
#Sta/Elev= 30
       0  803.52    18.5  789.89    92.6  738.48   129.7  716.19   178.6  689.09
   217.8  673.24   227.6  670.76   247.1  667.62   325.4  651.35   335.2  650.24
     345   650.1   364.6  650.47   384.2   655.1   403.8  656.36   442.9  657.74
   501.6  657.94     531  658.82     580  657.51   619.1  657.67   638.7  659.22
   668.1  663.38   687.6  664.37   804.6  661.13   950.6  661.74   970.1   662.9
   999.3  668.78    1009  670.15  1028.5   671.2  1038.2  672.44  1096.7  682.32
#Mann= 3 , 0 , 0
       0      .1       0   335.2    .045       0   364.6     .06       0
Bank Sta=335.2,364.6
XS Rating Curve= 0 ,0
Exp/Cntr=0.3,0.1

Chan Stop Cuts=-1
Use User Specified Reach Order=0
Composite Channel Slope=5